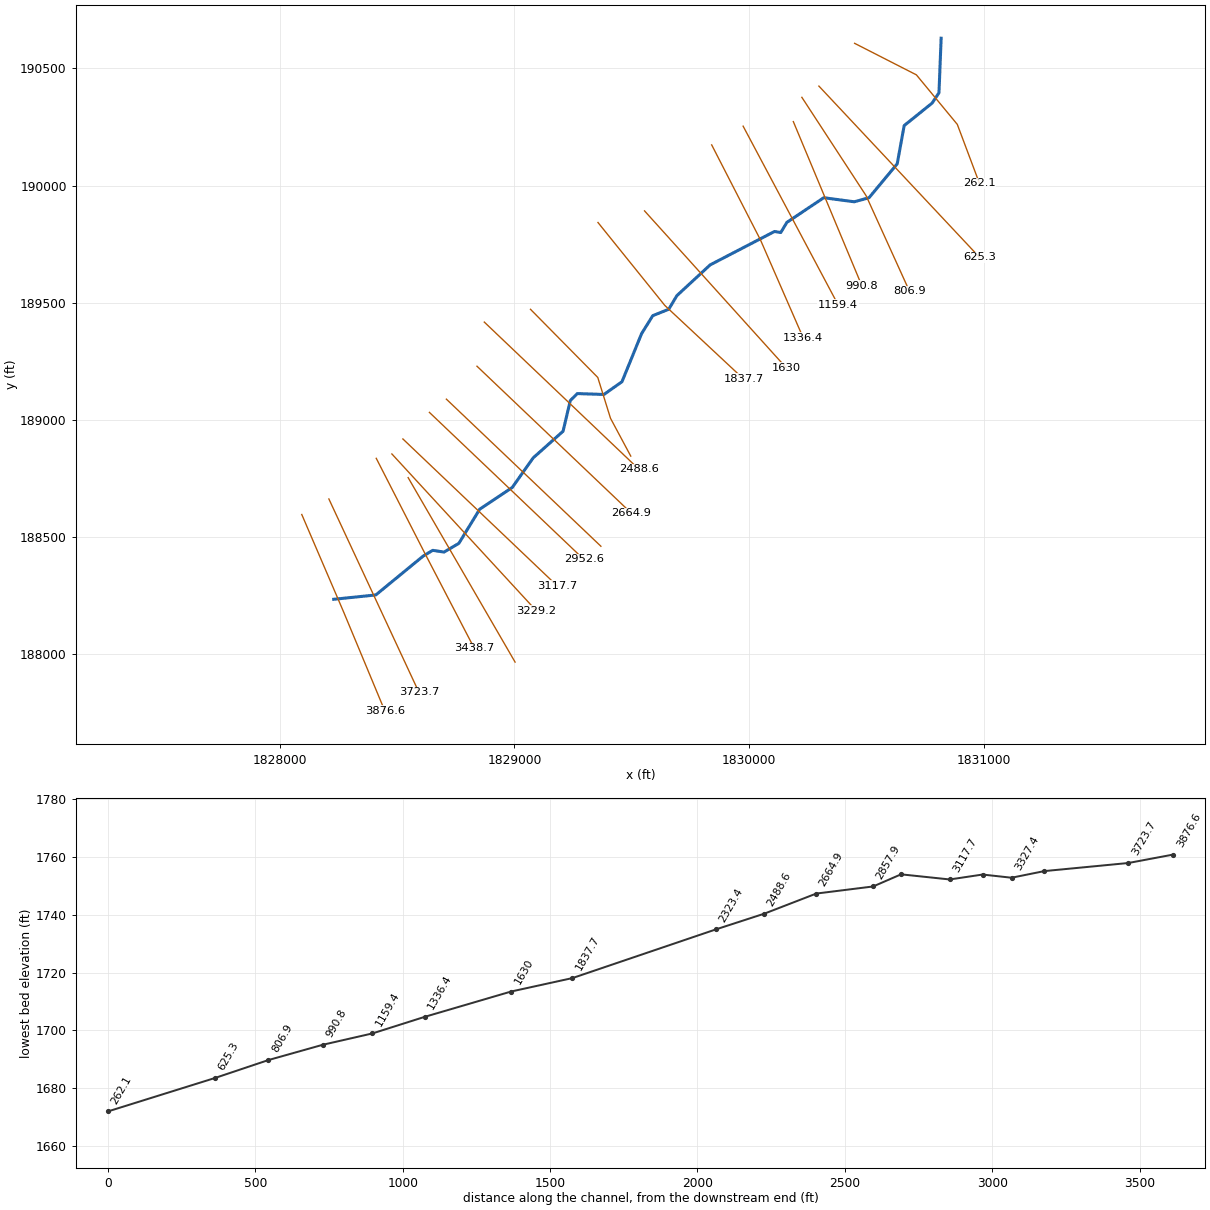
--- JennyBr.prj (project) ---

Proj Title=JennyBr
Current Plan=p01
Default Exp/Contr=0,0
English Units
Geom File=g01
Flow File=f01
Plan File=p01
BEGIN DESCRIPTION:
END DESCRIPTION:
DSS Export Rating Curves= 0
DSS Export Rating Curve Sorted= 0
DSS Export Volume Flow Curves= 0
DXF OffsetX= 0
DXF OffsetY= 0
DXF ScaleX= 0
DXF ScaleY= 0

--- JennyBr.p01 (plan) ---

Plan Title=Floodplain
Program Version=4.00
Geom File=g01
Flow File=f01
K Sum by GR=0
Std Step Tol=0.01
Critical Tol=0.01
Num of Std Step Trials=20
Max Error Tol=0.3
Flow Tol Ratio=0.001
Split Flow NTrial=30
Split Flow Tol=0.02
Split Flow Ratio=0.02
Log Output Level=0
Friction Slope Method=1
Unsteady Friction Slope Method=2
Unsteady Bridges Friction Slope Method=1
Global Log Level=0
CheckData=False
Run HTab=0
Run UNet=0
Run PostProcess=0
UNET Theta=0
UNET Theta Warmup=0
UNET ZTol=0
UNET ZSATol=0
UNET MxIter=0
UNET MaxInSteps=0
UNET DtIC=0
UNET DtMin=0
UNET MaxCRTS=0
UNET WFStab=0
UNET SFStab=0
UNET WFX=0
UNET SFX=0
UNET DSS MLevel=0
UNET DZMax Abort=0
UNET Convert EG Bridges=0
UNET Use Existing IB Tables=0
UNET Froude Limit=0
UNET Froude Power=0
Write IC File=0
Echo Input=False
Echo Output=False
Write Detailed=0

--- JennyBr.f01 (steady flow) ---

Flow Title=NFF Regression Equation
Program Version=4.00
Number of Profiles=1
Profile Names=P100yr
River Rch & RM=JennyBr,Main      ,3876.6
391.3806
River Rch & RM=JennyBr,Main      ,3438.7
603.9369
River Rch & RM=JennyBr,Main      ,2664.9
633.5430
River Rch & RM=JennyBr,Main      ,262.1
691.4120
Boundary for River Rch & Prof#=JennyBr,Main      ,1
Up Type=0
Dn Type=3
Dn Slope=0.028985

--- JennyBr.g01 (geometry) ---

Geom Title=USGS 10m DEM
Program Version=4.00

River Reach=JennyBr         ,Main
Reach XY= 30
     1828230.071      188233.374     1828409.459      188251.932
     1828611.115      188417.711     1828651.941      188442.454
     1828700.191      188435.031     1828763.286      188472.145
     1828852.361       188618.13     1828990.923      188710.917
     1829079.998      188837.107     1829207.425      188950.925
     1829238.354      189082.064     1829268.046      189111.756
     1829381.864      189108.044     1829458.568      189162.479
     1829542.009      189367.529     1829589.707      189444.551
      1829657.75      189471.768     1829692.391      189529.915
     1829834.222      189661.303     1830108.621      189804.025
     1830135.293      189799.615     1830161.273      189842.916
     1830318.392      189948.074     1830448.293      189930.754
     1830511.388      189948.074     1830631.393      190092.821
     1830661.085      190256.126     1830780.243       190352.23
     1830809.413      190396.271     1830818.644      190629.226

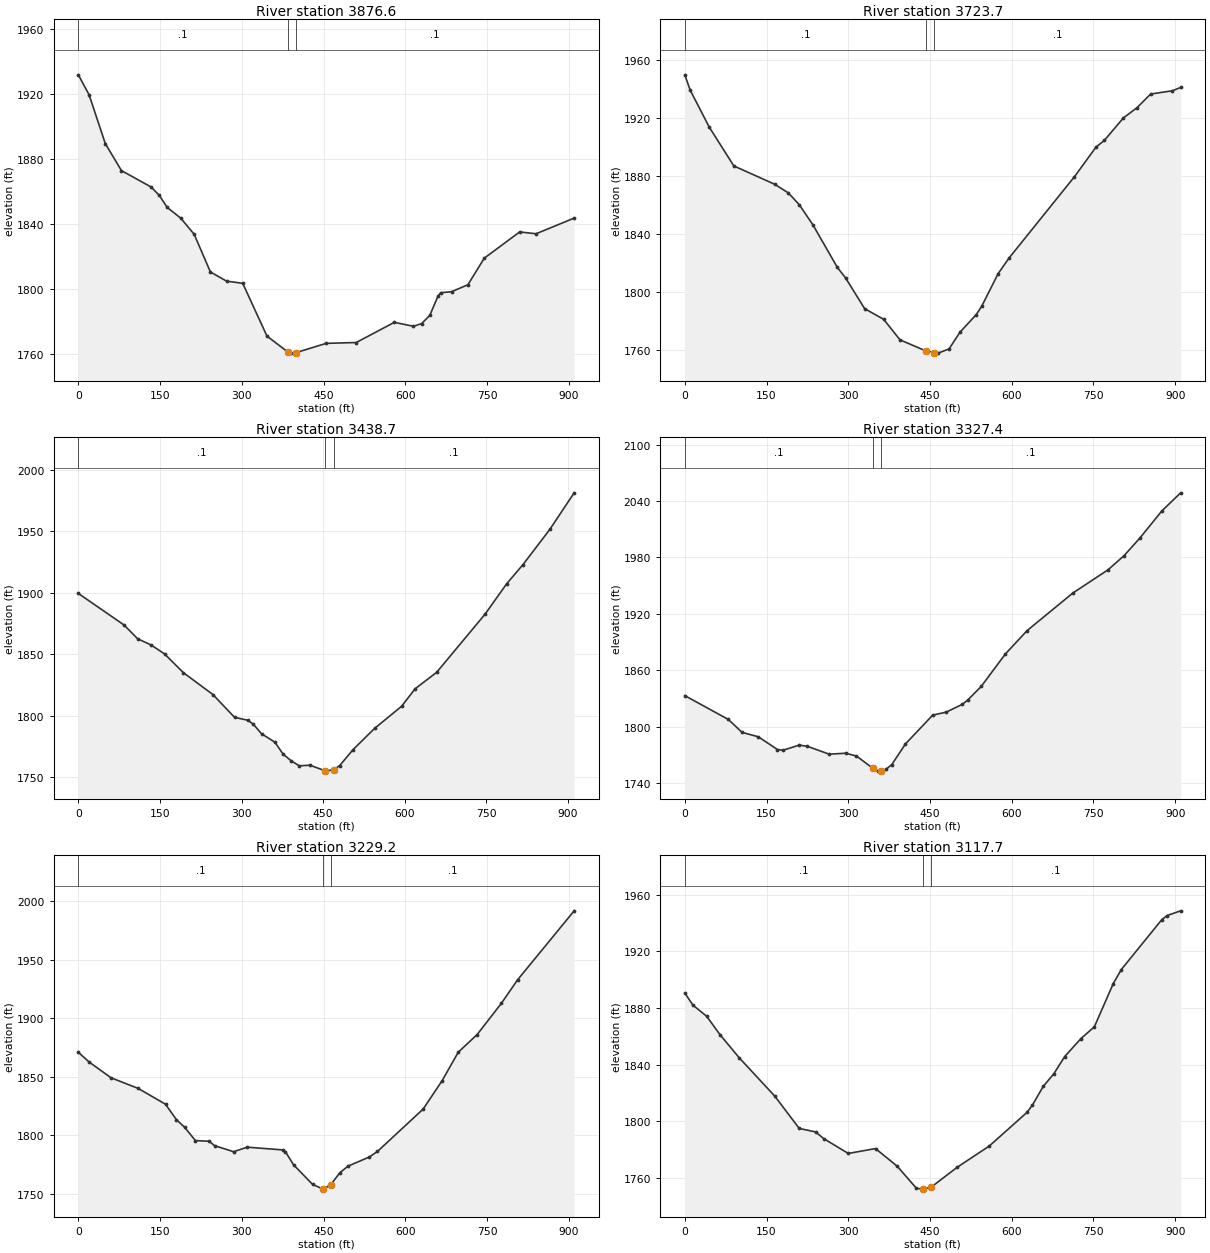
Type RM Length L Ch R = 1 ,3876.6  ,151,152.9,154.7
XS GIS Cut Line= 3
      1828094.01      188595.409     1828273.205      188177.145
     1828447.812      187756.988
#Sta/Elev= 30
       0 1932.03    19.8  1919.7    49.5 1889.72    79.1 1873.12   133.5 1863.04
   148.4 1857.91   163.2 1850.44     188 1843.86   212.7 1833.86   242.4 1810.76
     272 1805.12   301.7 1803.77   346.2 1771.31   384.5 1761.51   390.7 1760.82
   399.5 1761.13     455 1766.83     510 1767.35     580 1779.76     615 1777.34
     630 1778.99     645 1784.03     660  1795.8     665 1797.97     685 1798.61
     715 1802.89     745 1819.22     810 1835.38     840 1834.25     910 1843.88
#Mann= 3 , 0 , 0
       0      .1       0   384.5    .045       0   399.5      .1       0
Bank Sta=384.5,399.5
XS Rating Curve= 0 ,0
Exp/Cntr=0.3,0.1

Type RM Length L Ch R = 1 ,3723.7  ,285,285,285.1
XS GIS Cut Line= 3
     1828209.413      188661.874     1828401.219      188249.278
     1828593.025      187836.682
#Sta/Elev= 30
       0 1949.48      10 1938.84      45 1913.41      90 1886.76     165 1874.15
     190 1868.19     210 1860.11     235 1846.28     280  1816.9     295  1809.7
     330 1788.54     365 1781.14     395 1767.03   443.2 1759.29   458.2 1758.28
     465 1757.89     485 1760.81     505 1772.27     535 1784.45     545 1790.21
     575 1812.56     595 1823.32     715 1879.27     755 1899.86     770 1904.32
     805 1919.82     830 1926.88     855 1936.26     895 1938.51     910 1940.79
#Mann= 3 , 0 , 0
       0      .1       0   443.2    .045       0   458.2      .1       0
Bank Sta=443.2,458.2
XS Rating Curve= 0 ,0
Exp/Cntr=0.3,0.1

Type RM Length L Ch R = 1 ,3438.7  ,110.4,111.3,112.2
XS GIS Cut Line= 3
     1828411.407      188835.301     1828618.569      188429.516
     1828828.709      188024.837
#Sta/Elev= 30
       0 1899.59    84.2 1873.88     109 1862.74   133.7 1857.69   158.5 1850.42
   193.1 1835.17   247.6 1817.31   287.2 1798.83     312 1796.43   321.9 1793.15
   336.8 1785.49   361.5 1778.58   376.4 1768.95   391.2 1763.54   406.1  1759.4
   425.9 1759.91   454.4 1755.26   455.6 1755.09   469.4 1756.37   480.4 1759.54
   505.2 1772.62   544.8 1789.88   594.4 1807.84   619.2 1822.06   658.8 1835.43
     748 1882.85   787.7 1907.56   817.4 1922.96     867 1951.74   911.6  1981.4
#Mann= 3 , 0 , 0
       0      .1       0   454.4    .045       0   469.4      .1       0
Bank Sta=454.4,469.4
XS Rating Curve= 0 ,0
Exp/Cntr=0.3,0.1

Type RM Length L Ch R = 1 ,3327.4  ,93.3,98.2,103
XS GIS Cut Line= 3
     1828547.274      188752.946     1828775.118      188359.103
     1829002.962      187965.261
#Sta/Elev= 30
       0  1833.1      80 1807.72     105 1794.03     135  1789.3     170 1775.78
     180 1774.96     210 1780.48     225 1779.18     265 1770.83     295 1771.83
     315  1768.9   345.5 1755.65     355  1752.8   360.5 1752.88     370 1755.09
     380 1759.83     405 1781.74     455 1812.36   479.7 1815.52   509.4 1823.83
   519.3 1828.42     544 1842.86   588.5 1877.46   628.1 1902.18   712.2 1942.19
   776.5 1966.76   806.1 1981.85   835.8 2001.04   875.4  2029.4     910 2048.74
#Mann= 3 , 0 , 0
       0      .1       0   345.5    .045       0   360.5      .1       0
Bank Sta=345.5,360.5
XS Rating Curve= 0 ,0
Exp/Cntr=0.3,0.1

Type RM Length L Ch R = 1 ,3229.2  ,109.7,111.5,113.3
XS GIS Cut Line= 3
     1828477.946      188854.023      1828785.87      188519.049
     1829093.795      188184.075
#Sta/Elev= 30
       0 1870.77      20 1862.39      60 1849.01     110 1839.88     160 1826.41
     180 1813.24     195 1806.75     215 1795.33     240  1794.8     250 1791.04
     285 1785.86     310 1789.74     375  1787.4     380 1785.93     395 1774.68
     430 1757.91   448.3 1754.09     450  1753.9   463.3 1757.68   479.7 1767.75
   494.6 1773.45   534.1 1781.35     549 1786.07     633 1822.36   667.7 1846.53
   697.3 1870.84     732 1885.95   776.5 1912.63   806.1 1932.63     910 1991.59
#Mann= 3 , 0 , 0
       0      .1       0   448.3    .045       0   463.3      .1       0
Bank Sta=448.3,463.3
XS Rating Curve= 0 ,0
Exp/Cntr=0.3,0.1

Type RM Length L Ch R = 1 ,3117.7  ,165.1,165.1,165.1
XS GIS Cut Line= 3
     1828524.923      188917.956     1828854.165       188603.91
     1829183.407      188289.864
#Sta/Elev= 30
       0 1890.63      15 1881.99      40 1874.25      65 1861.01     100 1844.84
     165 1817.91     210 1795.03     240 1792.58     255 1787.84     300 1777.38
     350 1780.82     390 1768.32     425 1752.83     435  1752.2   436.6 1752.23
   451.6 1753.42   499.5 1767.52   558.9 1782.63   628.1 1806.39     638  1811.5
   657.8 1824.68   677.6 1833.79   697.3 1845.79     727 1858.42   751.7 1866.77
   786.4 1897.28   801.2 1907.18   875.4 1942.35   885.3 1945.27     910 1948.59
#Mann= 3 , 0 , 0
       0      .1       0   436.6    .045       0   451.6      .1       0
Bank Sta=436.6,451.6
XS Rating Curve= 0 ,0
Exp/Cntr=0.3,0.1

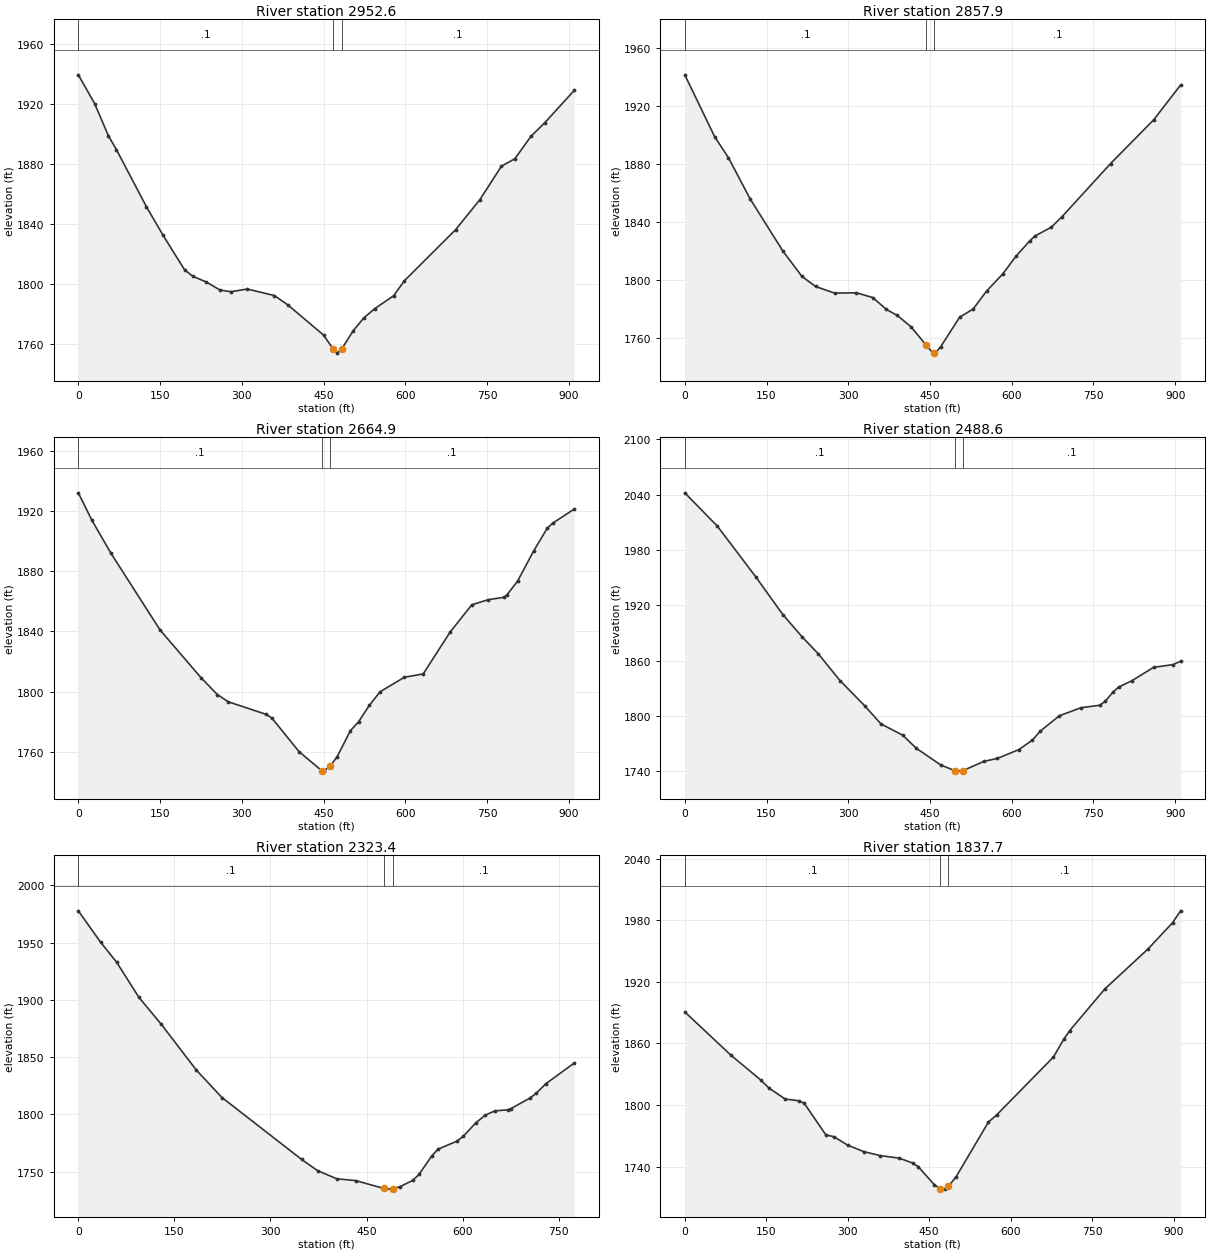
Type RM Length L Ch R = 1 ,2952.6  ,94.7,94.7,94.7
XS GIS Cut Line= 3
     1828637.925      189031.454     1828967.166      188717.408
     1829296.408      188403.362
#Sta/Elev= 30
       0 1939.31      30 1920.09      55  1898.9      70  1889.4     125 1851.45
     155 1832.76     195 1809.44     210 1805.19     235 1801.31     260    1796
     280 1794.85     310 1796.67     360 1792.28     385 1785.95     450 1766.01
   468.2 1756.44   474.8 1753.97   483.2  1756.6   504.5  1768.9   524.2  1777.5
     544 1783.59   578.6 1792.15   598.4 1802.17   692.4 1836.17   736.9 1856.15
   776.5 1878.43   801.2 1883.44   830.9 1898.44   855.6 1907.21     910  1928.9
#Mann= 3 , 0 , 0
       0      .1       0   468.2    .045       0   483.2      .1       0
Bank Sta=468.2,483.2
XS Rating Curve= 0 ,0
Exp/Cntr=0.3,0.1

Type RM Length L Ch R = 1 ,2857.9  ,193,193,193
XS GIS Cut Line= 3
     1828710.254      189087.934     1829039.496      188773.888
     1829368.738      188459.842
#Sta/Elev= 30
       0 1941.38      55 1898.62      80  1884.4     120 1855.91     180 1820.08
     215 1802.58     240 1795.67     275 1791.09     315  1791.3     345 1788.05
     370 1779.86     390 1775.74     415 1767.96   443.1 1755.23     455 1749.93
   458.1 1749.84     460 1749.78   469.8  1754.3   504.5 1774.54   529.2 1780.12
   553.9 1792.52   583.6 1804.31   608.3  1816.7     633 1827.03   642.9 1830.47
   672.6 1836.46   692.4 1843.74   781.4 1880.29   860.5 1910.38     910 1934.38
#Mann= 3 , 0 , 0
       0      .1       0   443.1    .045       0   458.1      .1       0
Bank Sta=443.1,458.1
XS Rating Curve= 0 ,0
Exp/Cntr=0.3,0.1

Type RM Length L Ch R = 1 ,2664.9  ,177.9,176.3,174.8
XS GIS Cut Line= 3
     1828840.543      189228.649     1829169.785      188914.603
     1829499.027      188600.557
#Sta/Elev= 30
       0 1931.93      25 1913.66      60 1891.76     150 1840.95     225 1809.38
     255 1798.14     275 1793.34     345 1784.94     355 1782.62     405 1760.29
   446.9 1747.57     450 1747.32   461.9 1750.57   474.8 1756.78   499.5 1774.23
   514.4 1780.06   534.1 1790.97   553.9 1799.99   598.4 1809.58     633 1811.81
   682.5 1839.65   722.1 1857.63   751.7    1861   781.4 1862.66   786.4 1864.11
   806.1 1873.33   835.8 1893.45   860.5 1908.41   870.4 1911.74     910 1921.14
#Mann= 3 , 0 , 0
       0      .1       0   446.9    .045       0   461.9      .1       0
Bank Sta=446.9,461.9
XS Rating Curve= 0 ,0
Exp/Cntr=0.3,0.1

Type RM Length L Ch R = 1 ,2488.6  ,175.6,165.2,154.8
XS GIS Cut Line= 3
     1828871.818      189417.068      1829201.06      189103.022
     1829530.302      188788.976
#Sta/Elev= 30
       0 2041.86      60 2005.61     130 1951.01     180 1909.92     215 1886.04
     245 1867.45     285 1838.33     330 1811.29     360 1791.54     400 1779.27
     425 1765.06   469.8 1747.02     496 1740.78   499.5 1740.37     511 1741.03
     549 1750.94   573.7 1754.12   613.3 1763.75     638 1774.04   652.8 1783.86
   687.4 1800.34     727 1809.02   761.6 1811.73   771.5 1815.97   786.4 1826.33
   796.2 1831.33     821 1838.46   860.5 1852.82   895.2 1855.66     910 1859.32
#Mann= 3 , 0 , 0
       0      .1       0     496    .045       0     511      .1       0
Bank Sta=496,511
XS Rating Curve= 0 ,0
Exp/Cntr=0.3,0.1

Type RM Length L Ch R = 1 ,2323.4  ,473.3,485.7,497.9
XS GIS Cut Line= 4
     1829068.619      189471.694     1829355.323      189180.716
     1829409.635      189006.345     1829495.868      188844.837
#Sta/Elev= 30
       0 1977.66    34.9 1950.18    59.8 1932.85    94.6 1902.18   129.5  1878.7
   184.3 1838.72   224.2 1814.82   348.7  1760.8   373.6    1751   403.5 1743.94
   433.2 1742.31   476.9 1735.53   487.5  1734.9   491.9 1735.22   502.3 1737.06
     522 1742.45   531.9  1747.7   551.6 1763.63   561.5  1769.7   591.1 1776.71
     601 1780.96   620.8 1792.81   635.7 1799.52   650.5 1803.16   670.3 1804.07
   675.2 1805.08   704.9 1814.22   714.8 1818.42   729.7 1826.71   774.2 1844.85
#Mann= 3 , 0 , 0
       0      .1       0   476.9    .045       0   491.9      .1       0
Bank Sta=476.9,491.9
XS Rating Curve= 0 ,0
Exp/Cntr=0.3,0.1

Type RM Length L Ch R = 1 ,1837.7  ,210,207.7,205.6
XS GIS Cut Line= 3
     1829356.299      189842.203     1829641.182      189488.098
     1829976.039      189174.803
#Sta/Elev= 30
       0 1890.75    84.9 1848.59   139.8 1824.46   154.8  1816.6   184.8 1805.88
   209.8 1804.19   219.8 1801.84   259.7 1770.99   274.7 1769.14   299.6 1761.04
   329.6 1754.62   359.6 1750.79   394.6 1748.32   419.5 1743.54   429.5 1740.13
   459.5 1722.39   470.2 1718.58   474.4  1718.1   479.4 1718.13   485.2 1720.74
   499.3 1729.91   559.2 1783.51   574.1 1790.31   678.8  1846.8   698.7 1864.83
   708.7 1872.48   773.5 1913.17   853.2  1952.2   898.1 1977.65     913 1989.23
#Mann= 3 , 0 , 0
       0      .1       0   470.2    .045       0   485.2      .1       0
Bank Sta=470.2,485.2
XS Rating Curve= 0 ,0
Exp/Cntr=0.3,0.1

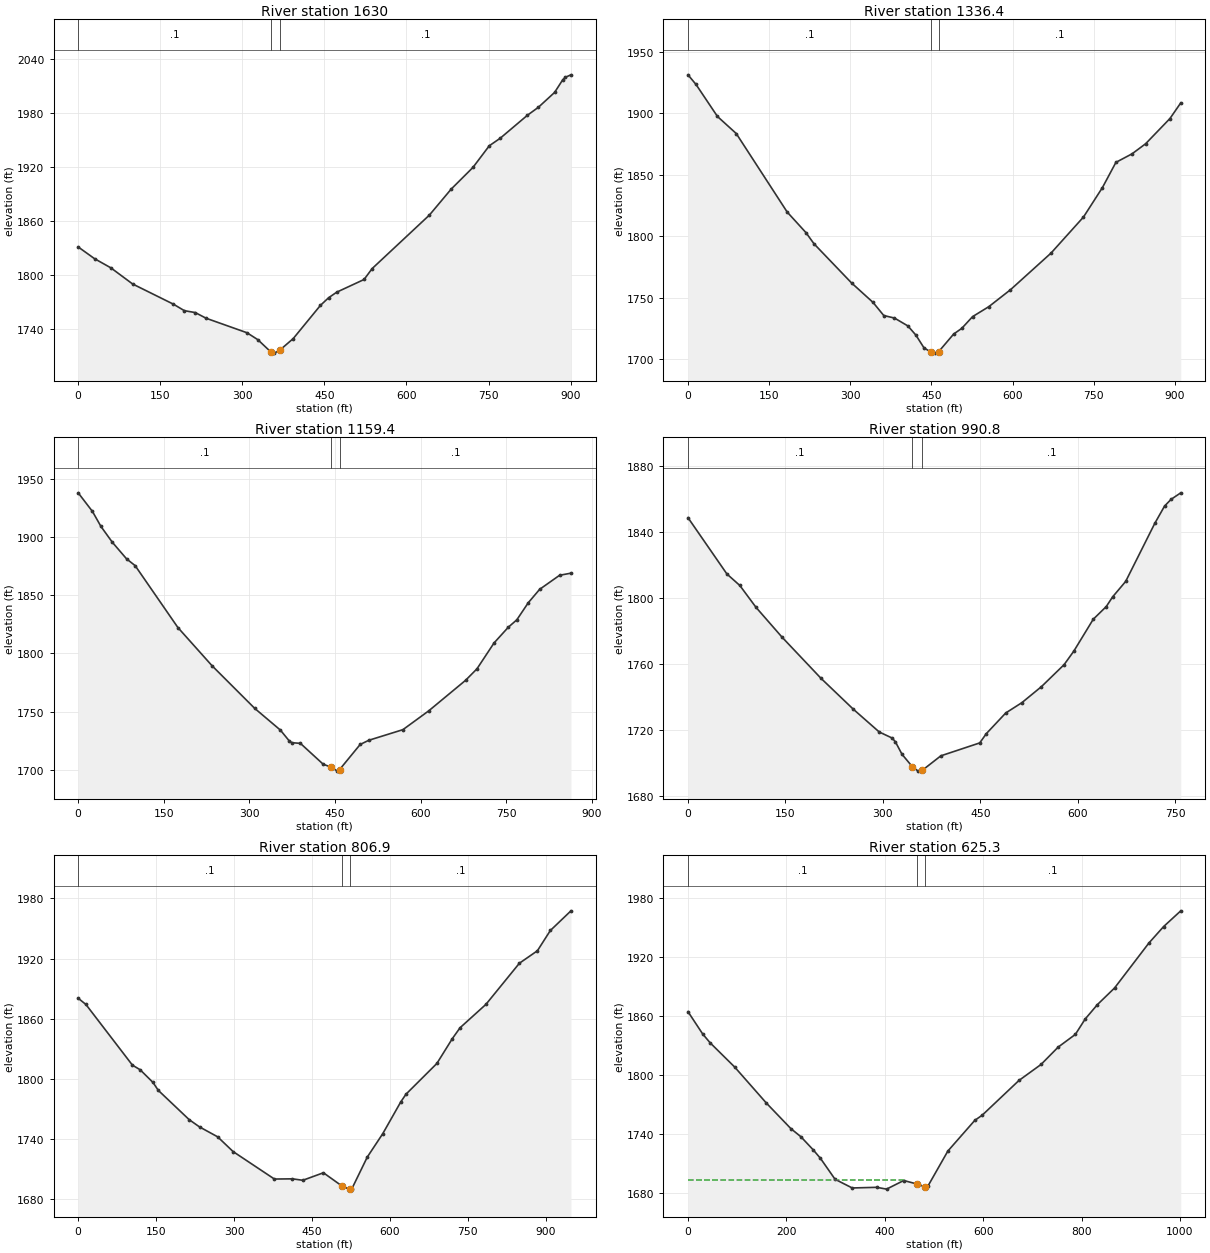
Type RM Length L Ch R = 1 ,1630    ,299.4,293.6,286.3
XS GIS Cut Line= 2
     1829554.689        189891.9     1830157.631      189222.829
#Sta/Elev= 30
       0 1831.23    29.9 1818.22    59.7 1808.07    99.5 1790.16   174.2 1767.71
   194.1 1760.54     214 1758.44   233.9 1752.14   308.5 1736.07   328.4 1728.36
   353.1 1714.22   358.3 1713.46   368.1 1716.56   393.1 1729.62   442.9 1766.51
   457.8 1774.93   472.7 1781.11   522.5 1795.13   537.4  1807.3   641.9 1866.55
   681.7 1895.35   721.5 1919.41   751.4 1943.45   771.3 1951.77     821 1977.26
     841 1986.07   870.8 2002.64   885.7 2016.69   890.7  2019.5   900.7 2022.14
#Mann= 3 , 0 , 0
       0      .1       0   353.1    .045       0   368.1      .1       0
Bank Sta=353.1,368.1
XS Rating Curve= 0 ,0
Exp/Cntr=0.3,0.1

Type RM Length L Ch R = 1 ,1336.4  ,177.6,177,179.5
XS GIS Cut Line= 3
     1829840.785       190173.77     1830048.738       189767.85
     1830230.335      189350.869
#Sta/Elev= 30
       0 1931.45    14.9 1923.57    54.5  1897.5    89.2 1883.63   183.4 1819.62
   218.1 1802.87     233 1793.75   302.4 1761.85   342.1    1746   361.9 1735.33
   381.7 1733.27   406.5 1726.84   421.4  1719.3   436.3 1708.94   448.6 1705.72
   456.1 1704.69   463.6 1706.01   491.1 1720.25   506.1 1724.88   526.1 1734.44
     556 1742.53     596  1756.3     671 1786.17     731 1815.55     766 1839.53
     791 1860.12   820.9  1867.1   845.9 1875.28   890.9 1895.85   910.9 1908.61
#Mann= 3 , 0 , 0
       0      .1       0   448.6    .045       0   463.6      .1       0
Bank Sta=448.6,463.6
XS Rating Curve= 0 ,0
Exp/Cntr=0.3,0.1

Type RM Length L Ch R = 1 ,1159.4  ,170,168.7,167.4
XS GIS Cut Line= 2
     1829974.804      190253.665     1830379.358      189491.235
#Sta/Elev= 30
       0  1937.9      25 1921.92    39.9 1909.01    59.9  1895.4    84.8 1881.19
    99.8 1875.38   174.6 1822.27   234.5 1789.43   309.3  1752.8   354.2 1734.18
   369.2 1725.19   374.2 1723.38   389.2 1722.82   429.1 1704.91   442.9 1702.38
     454 1698.97   457.9 1700.34   493.9 1721.85   508.9 1725.44   568.8 1734.58
   613.7 1750.62   678.5 1776.93   698.5 1786.83   728.4 1809.03   753.4 1822.54
   768.3 1828.89   788.3 1843.52   808.2 1855.03   843.2 1867.12   863.1 1868.93
#Mann= 3 , 0 , 0
       0      .1       0   442.9    .045       0   457.9      .1       0
Bank Sta=442.9,457.9
XS Rating Curve= 0 ,0
Exp/Cntr=0.3,0.1

Type RM Length L Ch R = 1 ,990.8   ,183.5,183.9,183.5
XS GIS Cut Line= 2
     1830188.751      190273.115     1830480.497      189572.924
#Sta/Elev= 30
       0 1848.71    59.9 1814.58    79.8  1807.6   104.8  1794.3   144.7 1776.29
   204.6 1751.36   254.5 1732.57   294.4 1718.76   314.4 1715.07   319.4 1712.71
   329.4 1705.26   345.5 1697.64   354.3 1695.04   360.5  1695.5   389.2 1704.31
   449.1 1712.15   459.1 1717.73   489.1  1730.3     514 1736.57     544 1746.25
   578.9 1759.59   593.9 1767.81   623.8 1787.14   643.8 1794.81   653.7 1800.74
   673.7 1810.07   718.6 1845.35   733.6 1855.78   743.6 1859.84   758.5 1863.78
#Mann= 3 , 0 , 0
       0      .1       0   345.5    .045       0   360.5      .1       0
Bank Sta=345.5,360.5
XS Rating Curve= 0 ,0
Exp/Cntr=0.3,0.1

Type RM Length L Ch R = 1 ,806.9   ,174.2,181.6,189.8
XS GIS Cut Line= 3
     1830225.117      190376.803     1830499.122      189956.267
      1830683.45      189549.445
#Sta/Elev= 30
       0 1880.36    14.9 1874.12   104.4 1813.56   119.3 1808.94   144.1 1796.24
   154.1 1788.43   213.7 1759.12   233.6 1751.87   268.4 1742.01   298.2 1727.27
   377.7 1699.84   412.5 1700.04   432.4  1698.6   472.1  1706.1   507.6 1692.95
   521.8 1689.77   522.6 1689.81   526.7 1690.01   556.5 1721.76   586.3 1745.13
     621 1776.87     631 1784.53   690.5 1815.25   720.3 1840.08   735.2 1850.93
   784.8 1874.17   849.3 1915.28     884 1927.74   908.9 1947.97   948.6 1967.61
#Mann= 3 , 0 , 0
       0      .1       0   507.6    .045       0   522.6      .1       0
Bank Sta=507.6,522.6
XS Rating Curve= 0 ,0
Exp/Cntr=0.3,0.1

Type RM Length L Ch R = 1 ,625.3   ,365.1,363.2,361.2
XS GIS Cut Line= 2
     1830297.669      190424.822       1830982.3      189693.512
#Sta/Elev= 30
       0  1864.3    29.9 1841.57    44.9 1832.65    94.7 1808.02   159.5 1771.13
   209.3 1745.12   229.3 1737.03   254.2 1723.77   269.1 1715.05     299 1693.59
   333.9 1684.74   383.8  1685.4   403.7 1683.56   438.6 1692.34   466.3 1688.66
   481.3 1685.93   488.4  1687.2   528.3 1722.34   583.1 1753.62   598.1 1758.84
   672.8 1794.22   717.7 1810.52   752.6 1828.23   787.5 1841.14   807.4 1856.76
   832.3 1871.48   867.2 1888.42     937 1934.21   966.9 1950.95  1001.8    1967
#Mann= 3 , 0 , 0
       0      .1       0   466.3    .045       0   481.3      .1       0
#XS Ineff= 2 , 0
          442.87 1692.48
Permanent Ineff=
       F       F
Bank Sta=466.3,481.3
XS Rating Curve= 0 ,0
Exp/Cntr=0.3,0.1

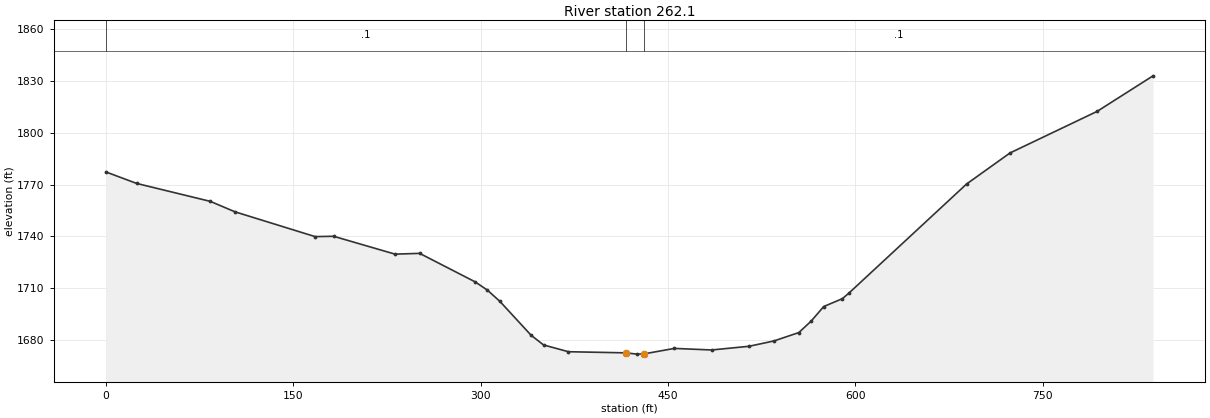
Type RM Length L Ch R = 1 ,262.1   ,246.1,262.1,278
XS GIS Cut Line= 4
     1830449.992      190607.367     1830713.133       190472.78
     1830887.504      190261.247     1830981.837      190009.695
#Sta/Elev= 30
       0 1777.27    24.6 1770.63    83.7 1760.24   103.4 1754.21   167.5  1739.9
   182.3 1740.09   231.5 1729.77   251.2 1730.22   295.6 1713.77   305.5 1708.95
   315.5 1702.45   340.4 1682.93   350.4 1677.31   370.3 1673.39   416.2 1672.74
   425.2    1672   431.2 1672.19   455.1  1675.3     485  1674.4   514.9 1676.53
   534.8  1679.6   554.8 1684.46   564.7  1691.1   574.7 1699.49   589.6 1704.02
   594.6 1707.06   689.1  1770.3   723.9 1788.24   793.6 1812.25   838.4  1832.8
#Mann= 3 , 0 , 0
       0      .1       0   416.2    .045       0   431.2      .1       0
#XS Ineff= 2 , 0
                           456.1         1675.26
Permanent Ineff=
       F       F
Bank Sta=416.2,431.2
XS Rating Curve= 0 ,0
Exp/Cntr=0.3,0.1

Chan Stop Cuts=-1
Use User Specified Reach Order=0